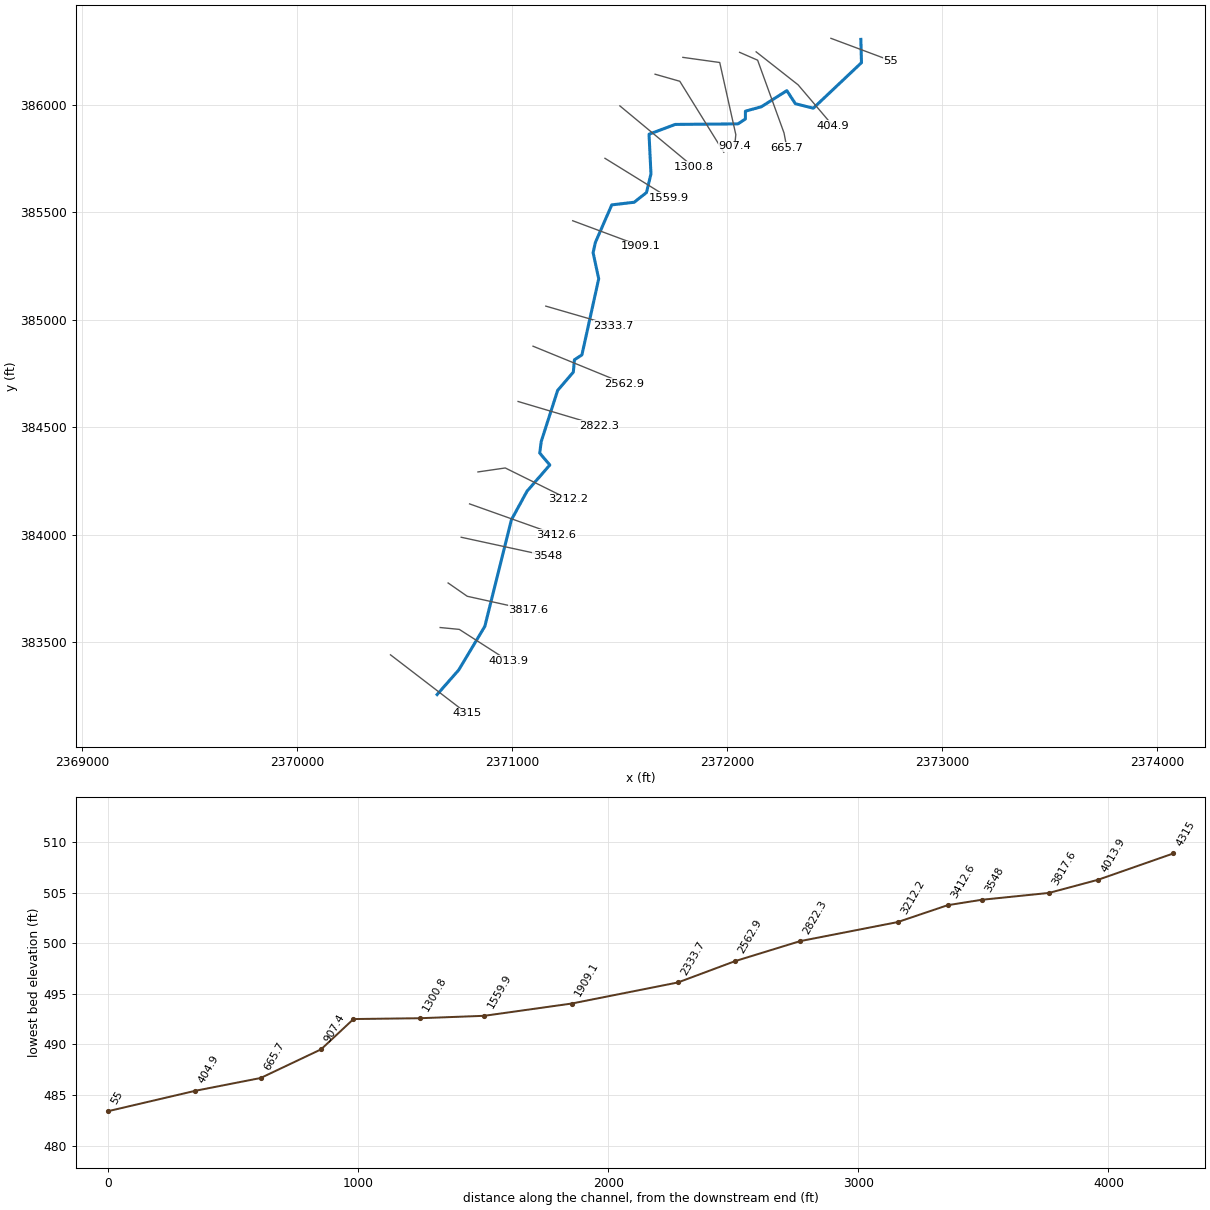
--- TILHNCTRIB.prj (project) ---

Proj Title=TILHNCTRIB
Current Plan=p01
Default Exp/Contr=0,0
English Units
Geom File=g01
Flow File=f01
Plan File=p01
BEGIN DESCRIPTION:
END DESCRIPTION:
DSS Export Rating Curves= 0
DSS Export Rating Curve Sorted= 0
DSS Export Volume Flow Curves= 0
DXF OffsetX= 0
DXF OffsetY= 0
DXF ScaleX= 0
DXF ScaleY= 0

--- TILHNCTRIB.p01 (plan) ---

Plan Title=Floodplain
Program Version=4.00
Geom File=g01
Flow File=f01
K Sum by GR=0
Std Step Tol=0.01
Critical Tol=0.01
Num of Std Step Trials=20
Max Error Tol=0.3
Flow Tol Ratio=0.001
Split Flow NTrial=30
Split Flow Tol=0.02
Split Flow Ratio=0.02
Log Output Level=0
Friction Slope Method=1
Unsteady Friction Slope Method=2
Unsteady Bridges Friction Slope Method=1
Global Log Level=0
CheckData=False
Run HTab=0
Run UNet=0
Run PostProcess=0
UNET Theta=0
UNET Theta Warmup=0
UNET ZTol=0
UNET ZSATol=0
UNET MxIter=0
UNET MaxInSteps=0
UNET DtIC=0
UNET DtMin=0
UNET MaxCRTS=0
UNET WFStab=0
UNET SFStab=0
UNET WFX=0
UNET SFX=0
UNET DSS MLevel=0
UNET DZMax Abort=0
UNET Convert EG Bridges=0
UNET Use Existing IB Tables=0
UNET Froude Limit=0
UNET Froude Power=0
Write IC File=0
Echo Input=False
Echo Output=False
Write Detailed=0

--- TILHNCTRIB.f01 (steady flow) ---

Flow Title=NFF Regression Equation
Program Version=4.10
Number of Profiles= 1
Profile Names=P100yr
River Rch & RM=TILHNCTRIB,Main            ,4315
547.6437
River Rch & RM=TILHNCTRIB,Main            ,1036.9
607.9521
River Rch & RM=TILHNCTRIB,Main            ,665.7
611.1371
Boundary for River Rch & Prof#=TILHNCTRIB,Main            , 1
Up Type= 0
Dn Type= 3
Dn Slope=0.007547
DSS Import GetInterval= 0
DSS Import GetPeak= 0
DSS Import FillOption= 0

--- TILHNCTRIB.g01 (geometry) ---

Geom Title=USGS 10m DEM
Program Version=4.10

River Reach=TILHNCTRIB      ,Main
Reach XY= 30
     2370651.686       383256.21     2370752.381      383370.793
     2370873.908      383573.918     2370997.172       384068.71
     2371070.089       384202.39     2371175.992      384323.918
     2371129.117      384379.473     2371136.061      384433.293
      2371212.45       384671.14     2371285.367      384756.209
     2371290.575      384813.501     2371325.297      384836.071
     2371403.422      385190.237     2371377.381      385311.765
     2371387.797       385358.64     2371464.186      385533.987
     2371568.353       385546.14     2371625.644      385591.279
     2371646.478      385678.085     2371637.499      385862.697
     2371759.447      385908.198     2372050.992      385910.724
     2372085.714      385933.293     2372085.714      385969.751
     2372160.367      385990.585     2372278.422      386065.237
     2372318.353      386004.473     2372401.686       385983.64
     2372625.645      386195.446      2372622.74      386303.719

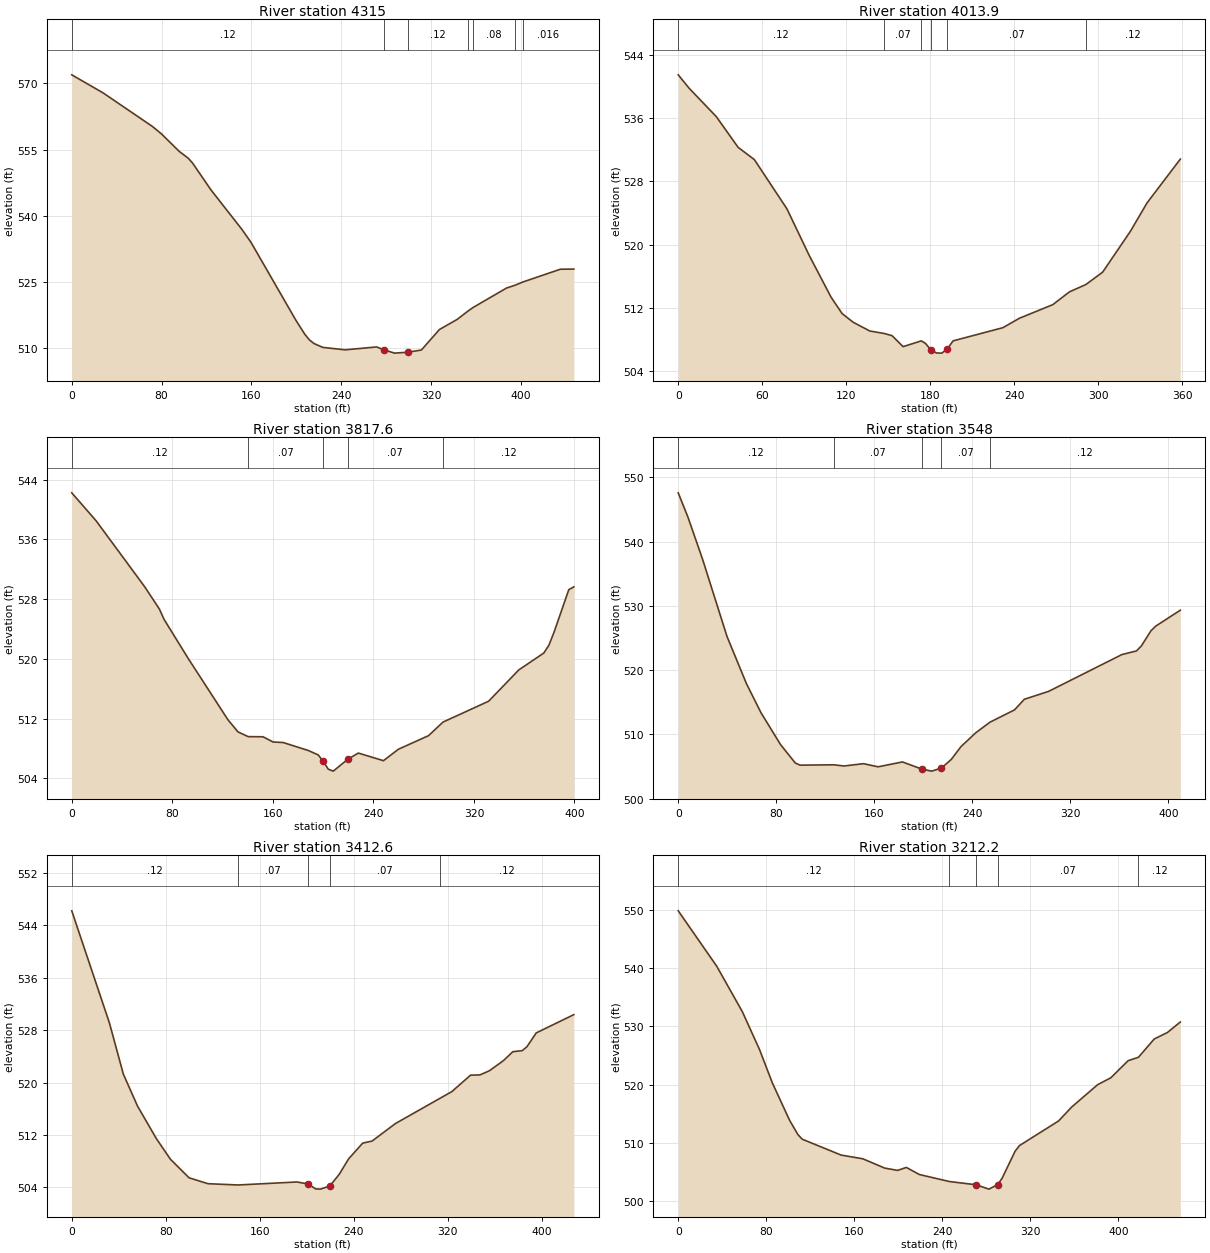
Type RM Length L Ch R = 1 ,4315    ,299,301.1,302.7
XS GIS Cut Line= 2
     2370434.923      383441.081      2370789.74      383168.728
#Sta/Elev= 30
       0  571.94      28  567.83    71.9  560.23    79.9  558.56    95.8  554.57
   103.8  553.04   107.8  551.88   123.8  545.93   151.8  536.83   159.8  533.92
   199.7   516.3   207.7  513.11   211.7  511.87   215.7  511.05   223.6  510.16
   243.6  509.61   271.6  510.26     278  509.62   287.6  508.86   299.5  509.07
   311.5  509.57   327.5   514.2   343.5  516.53  353.41518.4722   357.8 519.244
   387.4  523.62  394.54524.2134  402.05524.9949   435.3  527.88   447.3  527.91
#Mann= 7 ,-1 , 0
       0     .12       0     278    .045       0   299.5     .12       0
  353.41    .016       0   357.8     .08       0  394.54     .12       0
  402.05    .016       0
Bank Sta=278,299.5
XS Rating Curve= 0 ,0
Exp/Cntr=0.3,0.1

Type RM Length L Ch R = 1 ,4013.9  ,188.5,196.3,204.2
XS GIS Cut Line= 3
     2370666.042      383568.034     2370755.018      383559.353
     2370981.798      383413.954
#Sta/Elev= 30
       0  541.49     7.8  539.79    27.2   536.2    42.8  532.31    54.4  530.76
    77.7  524.52    93.4   518.7   109.2  513.35   117.1  511.27     125  510.17
   136.9  509.06  147.32508.7418   152.8  508.47   160.7  507.08   173.7  507.81
   176.6  507.51   180.5  506.68   184.5  506.28   188.4  506.26   192.4  506.82
   196.4  507.81     232  509.48   243.9  510.68   267.7   512.4   279.6  514.02
  291.33514.9439   303.3  516.51   323.1  521.67     335  525.27   358.8  530.82
#Mann= 6 ,-1 , 0
       0     .12       0  147.32     .07       0   173.7    .045       0
   180.5    .045       0   192.4     .07       0  291.33     .12       0
Bank Sta=180.5,192.4
XS Rating Curve= 0 ,0
Exp/Cntr=0.3,0.1

Type RM Length L Ch R = 1 ,3817.6  ,269.1,269.5,269.8
XS GIS Cut Line= 3
     2370702.935      383775.282      2370791.91      383713.433
     2371076.199      383650.499
#Sta/Elev= 30
       0  542.22    19.4  538.47      58  529.65    69.7  526.67    73.5  525.26
    92.9  519.98   124.3  511.83   132.3  510.21  140.38509.5794   152.2  509.56
   160.2  508.86   168.2  508.79   188.1  507.73   196.1  507.13   200.1  506.28
   204.1  505.22   208.1  504.96   219.4  506.52     228  507.38     248  506.36
   259.9  507.89   283.9  509.71  295.38511.5244   331.7  514.32   355.7  518.51
   375.6  520.77   379.6   521.8   383.6  523.49   395.5  529.26   399.5  529.63
#Mann= 5 ,-1 , 0
       0     .12       0  140.38     .07       0   200.1    .045       0
   219.4     .07       0  295.38     .12       0
Bank Sta=200.1,219.4
XS Rating Curve= 0 ,0
Exp/Cntr=0.3,0.1

Type RM Length L Ch R = 1 ,3548    ,138.6,135.5,132.4
XS GIS Cut Line= 2
     2370763.699      383987.956     2371164.089       383901.15
#Sta/Elev= 30
       0   547.6       8  543.78    19.9  537.24    39.8  525.24    55.7  517.88
    67.6  513.35    83.5  508.41    95.5  505.55    99.4  505.21  126.91505.2641
   135.2  505.08   151.2  505.44   163.1  504.95     183  505.71     199  504.58
   206.8  504.28   214.8  504.76   222.8   506.1   230.7  508.09   242.6  510.22
  254.36511.8946   274.4  513.81   282.4  515.46   302.3   516.7     362  522.42
   373.9  522.99   377.9  523.76   385.8  526.14   389.8  526.87   409.7  529.33
#Mann= 5 ,-1 , 0
       0     .12       0  126.91     .07       0     199    .045       0
   214.8     .07       0  254.36     .12       0
Bank Sta=199,214.8
XS Rating Curve= 0 ,0
Exp/Cntr=0.3,0.1

Type RM Length L Ch R = 1 ,3412.6  ,202.8,200.3,197.6
XS GIS Cut Line= 2
     2370802.761      384143.121     2371205.322      383999.891
#Sta/Elev= 30
       0  546.17      32  529.11    43.9  521.28    55.9  516.43    71.9  511.48
    83.9  508.32    99.8  505.48   115.8  504.58  141.45504.3811   191.7  504.84
   201.2  504.53   207.6  503.78   211.6  503.75   219.6  504.22   227.6     506
   235.6  508.36   247.6  510.76   255.6  511.08   275.5  513.75   313.7517.6255
   323.5  518.62   339.4  521.12   347.4  521.16   355.4  521.79   367.4  523.34
   375.4   524.7   383.4  524.86   387.4  525.46   395.3  527.56   427.3  530.35
#Mann= 5 ,-1 , 0
       0     .12       0  141.45     .07       0   201.2    .045       0
   219.6     .07       0   313.7     .12       0
Bank Sta=201.2,219.6
XS Rating Curve= 0 ,0
Exp/Cntr=0.3,0.1

Type RM Length L Ch R = 1 ,3212.2  ,381.4,389.9,395.9
XS GIS Cut Line= 3
     2370841.824      384291.775     2370968.777      384310.221
      2371262.83      384164.822
#Sta/Elev= 30
       0  549.79      35  540.29    58.3  532.49    73.9     526    85.5  520.31
   101.1  513.92   108.8  511.42   112.7  510.64     148  507.92   167.8  507.28
   187.6  505.69   199.4  505.29   207.3   505.8   219.2  504.58  246.48503.3807
   270.6  502.83   282.4  502.08   290.3  502.85   294.3  503.93   306.1  508.56
   310.1  509.54   345.7  513.77   357.5  516.14   381.2  519.99   393.1  521.16
   408.9   524.1  418.26 524.683   432.6  527.82   444.5  528.92   456.3  530.73
#Mann= 5 ,-1 , 0
       0     .12       0  246.48     .07       0   270.6    .045       0
   290.3     .07       0  418.26     .12       0
Bank Sta=270.6,290.3
XS Rating Curve= 0 ,0
Exp/Cntr=0.3,0.1

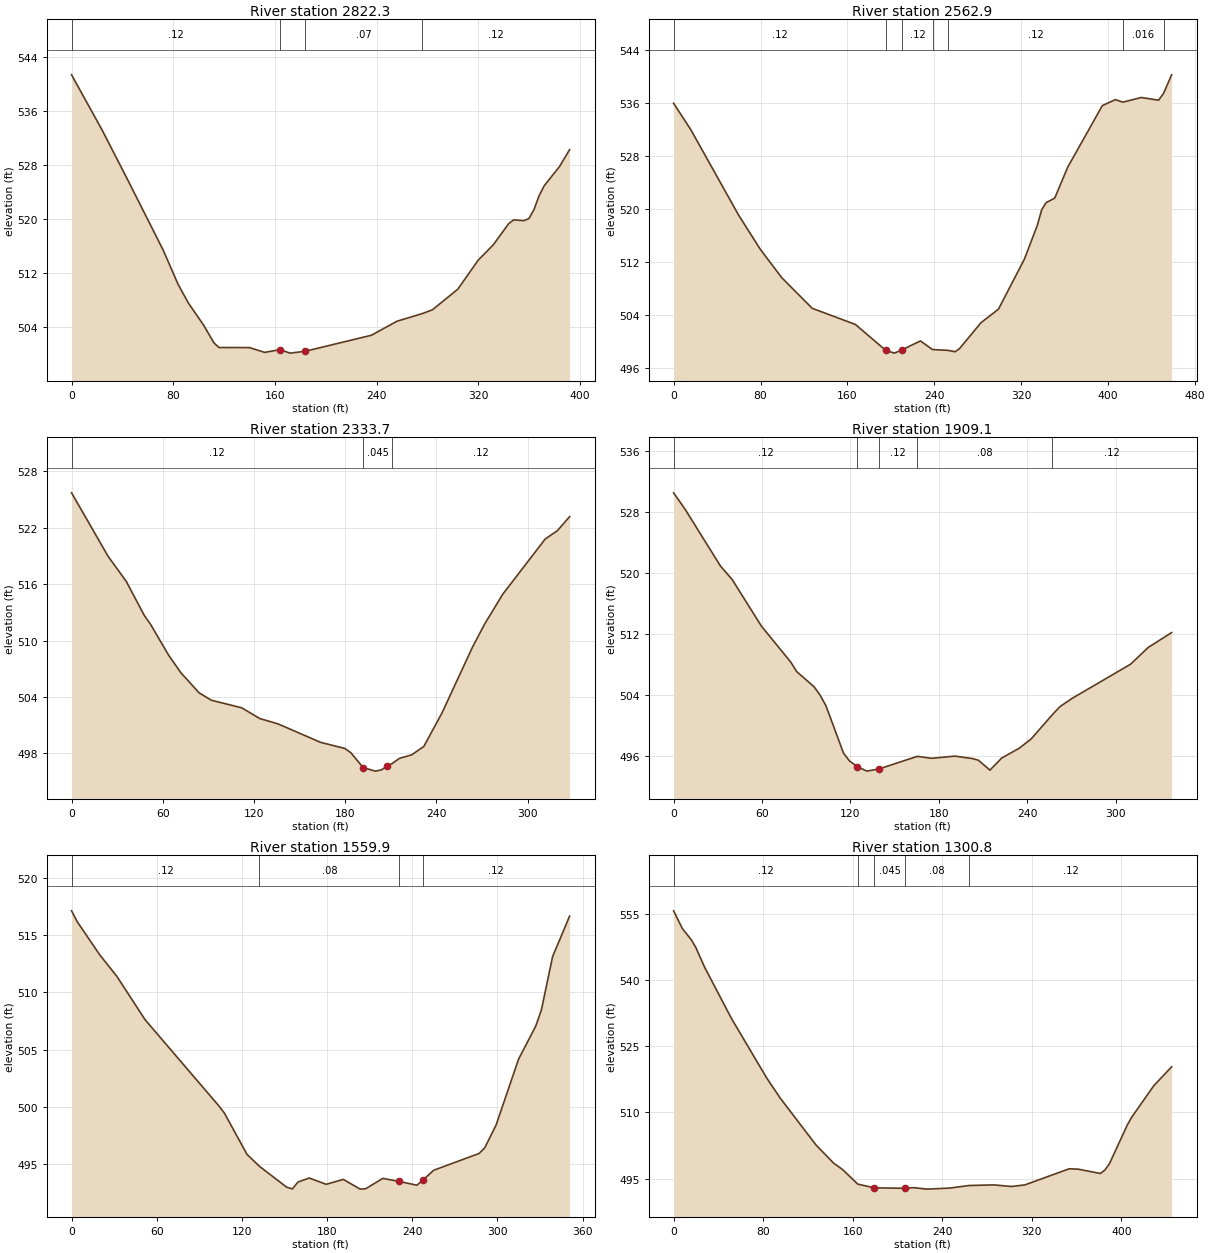
Type RM Length L Ch R = 1 ,2822.3  ,261.3,259.4,257.4
XS GIS Cut Line= 2
     2371028.455      384619.466      2371403.89      384507.704
#Sta/Elev= 30
       0  541.32      24  533.17      44  525.86      72  515.44    83.9  510.32
    91.9  507.59   103.9  504.33   111.9  501.73   115.9  501.03   139.9  501.02
   151.9  500.31   163.9  500.71   171.9   500.2   183.9  500.48   235.8  502.84
   255.8   504.9  275.96506.0524   283.8   506.6   303.8  509.65   319.8  513.93
   331.8  516.23   343.8  519.34   347.8  519.89   355.7  519.77   359.7  520.08
   363.7  521.42   367.7  523.45   371.7  524.92   383.7  527.75   391.7  530.27
#Mann= 4 ,-1 , 0
       0     .12       0   163.9    .045       0   183.9     .07       0
  275.96     .12       0
Bank Sta=163.9,183.9
XS Rating Curve= 0 ,0
Exp/Cntr=0.3,0.1

Type RM Length L Ch R = 1 ,2562.9  ,226.3,229.2,232
XS GIS Cut Line= 2
       2371097.9      384876.628     2371522.162      384703.016
#Sta/Elev= 30
       0  535.92    15.9  531.92    59.8  519.06    79.7  513.92    99.6   509.6
   127.6  504.99   167.4  502.55   195.4  498.63   203.3  498.23   210.4  498.74
   227.2  500.07  238.36498.7676  252.72498.6469   259.1  498.44   263.1   498.9
     283  502.83     299  504.86   322.9  512.41   334.8  517.52   338.8  519.85
   342.8  520.92   350.8  521.61   362.7  526.26   394.6  535.56   406.6  536.47
  413.51536.0854   430.5  536.79   446.4  536.38  450.98537.4147   458.4  540.21
#Mann= 7 ,-1 , 0
       0     .12       0   195.4    .045       0   210.4     .12       0
  238.36     .07       0  252.72     .12       0  413.51    .016       0
  450.98     .12       0
Bank Sta=195.4,210.4
XS Rating Curve= 0 ,0
Exp/Cntr=0.3,0.1

Type RM Length L Ch R = 1 ,2333.7  ,426.3,424.6,422.9
XS GIS Cut Line= 2
     2371157.362      385063.042     2371472.032      384971.897
#Sta/Elev= 30
       0   525.7      24  518.96      36  516.28    47.9  512.65    51.9  511.74
    63.9  508.43    71.9  506.58    83.9  504.44    91.9  503.66   111.9  502.85
   123.8  501.71   135.8  501.14   163.8  499.18   179.8  498.53   183.8  498.06
   191.8   496.5   199.8  496.12   203.8  496.25   207.8  496.68   210.9  496.93
   215.7  497.48   223.7  497.85   231.7  498.74   243.7  502.32   263.7  509.29
   271.7  511.75   283.7  514.94   311.6   520.8   319.6  521.68   327.6  523.17
#Mann= 3 ,-1 , 0
       0     .12       0   191.8    .045       0   210.9     .12       0
Bank Sta=191.8,207.8
XS Rating Curve= 0 ,0
Exp/Cntr=0.3,0.1

Type RM Length L Ch R = 1 ,1909.1  ,353.5,349.2,345.8
XS GIS Cut Line= 2
     2371282.506      385460.178     2371599.202      385342.122
#Sta/Elev= 30
       0  530.56       8  528.35    31.8  520.96    39.8  519.17    59.6  513.07
    79.5  508.35    83.5  507.11    95.4   505.1    99.4  504.02   103.4  502.62
   115.3  496.41   119.3  495.39   124.6  494.64   131.2  494.04   139.6  494.34
  165.46495.9807     175  495.72   190.9  496.01   202.8  495.69   206.8  495.48
   214.7  494.17   222.7  495.76   234.6  497.05   242.6  498.25  257.07501.4525
   262.4  502.53   270.4  503.58   310.2  508.08   322.1  510.27     338  512.22
#Mann= 5 ,-1 , 0
       0     .12       0   124.6    .045       0   139.6     .12       0
  165.46     .08       0  257.07     .12       0
Bank Sta=124.6,139.6
XS Rating Curve= 0 ,0
Exp/Cntr=0.3,0.1

Type RM Length L Ch R = 1 ,1559.9  ,260.7,259.1,255
XS GIS Cut Line= 2
     2371432.535      385750.542     2371730.929      385566.081
#Sta/Elev= 30
       0  517.13       4  516.18    19.9  513.28    31.9  511.41    51.8  507.62
   103.6  500.12   107.6  499.48   123.6  495.86  132.37494.8193   151.5     493
   155.5  492.85   159.5  493.45   167.4   493.8   179.4  493.25   191.4  493.68
   203.3  492.83   207.3  492.87   219.2  493.77   230.9   493.5   243.2  493.17
   247.2  493.59   255.1  494.48     287  495.94     291  496.43     299  498.42
   314.9  504.19   326.9  507.05   330.9  508.46   338.8  513.12   350.8  516.67
#Mann= 4 ,-1 , 0
       0     .12       0  132.37     .08       0   230.9    .045       0
   247.2     .12       0
Bank Sta=230.9,247.2
XS Rating Curve= 0 ,0
Exp/Cntr=0.3,0.1

Type RM Length L Ch R = 1 ,1300.8  ,270,263.9,257.8
XS GIS Cut Line= 2
     2371501.922      385994.401     2371844.287      385710.293
#Sta/Elev= 30
       0   555.8     7.9  551.75    15.9  549.21    19.9  547.46    27.8  542.95
    51.6  531.39    83.4  517.74    95.3  513.25   127.1  502.66     143  498.48
     151  497.03  164.52493.7264   179.4  492.88   206.6  492.78   214.5  492.92
   226.4  492.59   246.3  492.82  264.19493.4149     286  493.55   301.9  493.19
   313.8  493.55   353.5  497.22   361.5  497.12   381.3  496.14   385.3  496.93
   389.3  498.34   405.2  507.11   409.1  508.87     429  516.09   444.9  520.37
#Mann= 5 ,-1 , 0
       0     .12       0  164.52     .08       0   179.4    .045       0
   206.6     .08       0  264.19     .12       0
Bank Sta=179.4,206.6
XS Rating Curve= 0 ,0
Exp/Cntr=0.3,0.1

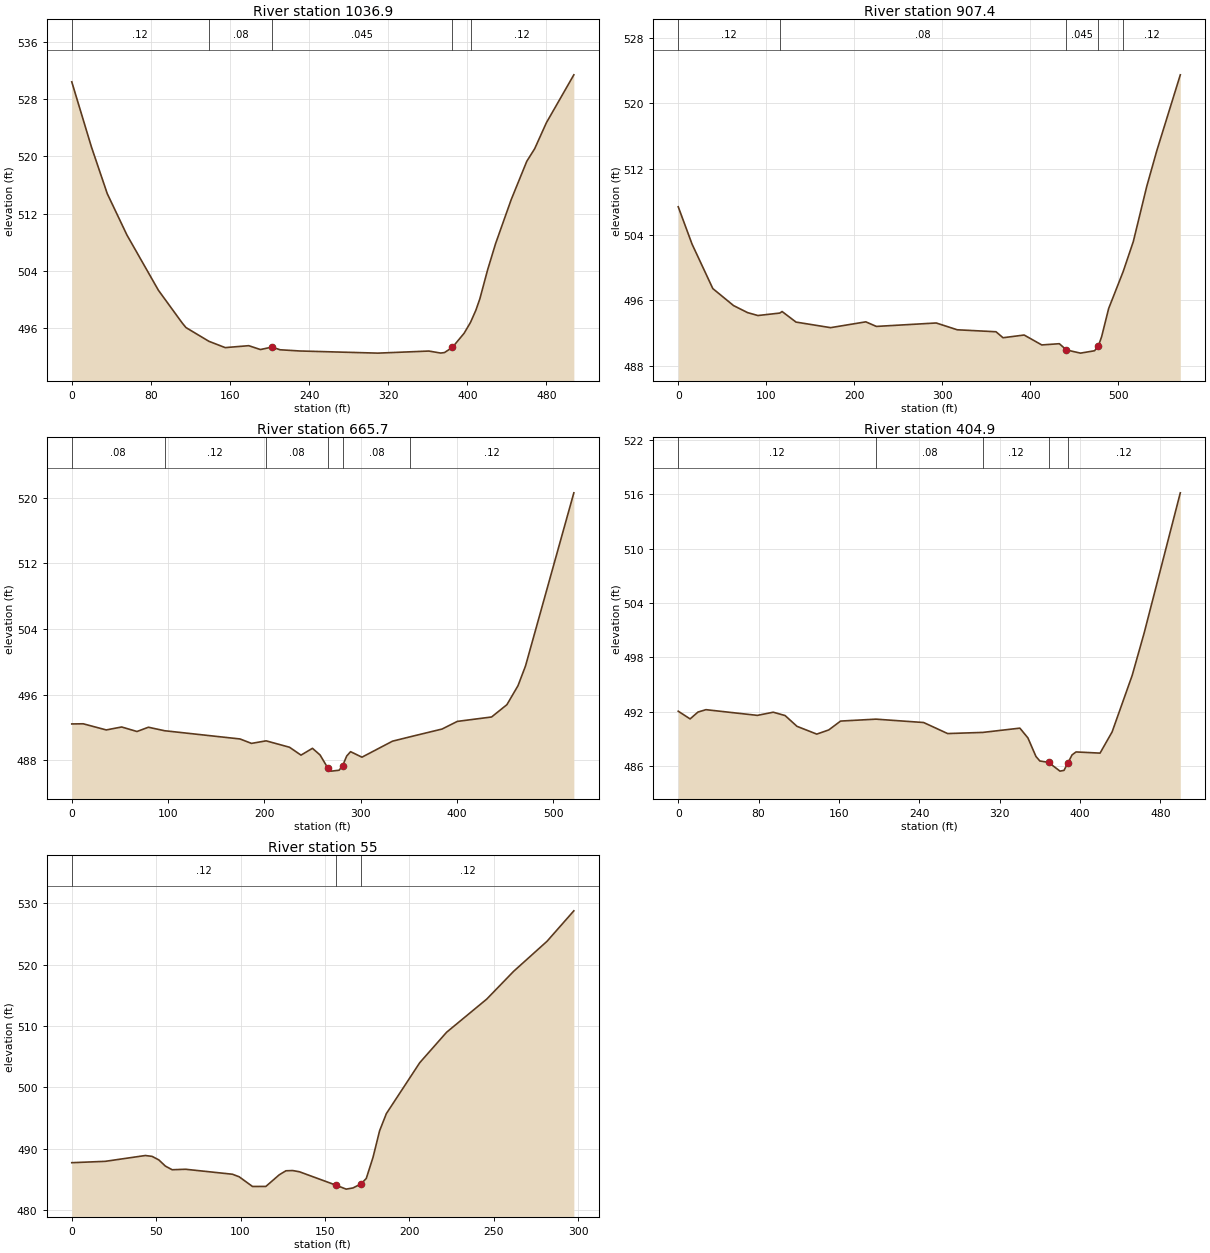
Type RM Length L Ch R = 1 ,1036.9  ,138,129.5,119.9
XS GIS Cut Line= 3
     2371665.697      386141.705     2371780.627      386108.892
     2371985.141      385778.858
#Sta/Elev= 30
       0  530.41    19.9  521.31    35.9  514.79    55.8  509.01    87.6   501.3
   111.6  496.74   115.5  496.08  138.74494.1588   155.2  493.28     179  493.55
   190.8  493.01   202.7  493.36   210.6  492.98   230.5  492.81   309.7  492.51
   361.2   492.8   373.1  492.52     377  492.59     385  493.32   396.8  495.28
  403.29496.8074   408.7   498.5   412.7  500.08   420.6  504.15   428.6  507.79
   444.4  513.94   460.2  519.31   468.2  521.07     480  524.69   507.8  531.39
#Mann= 5 ,-1 , 0
       0     .12       0  138.74     .08       0   202.7    .045       0
     385     .08       0  403.29     .12       0
Bank Sta=202.7,385
XS Rating Curve= 0 ,0
Exp/Cntr=0.3,0.1

Type RM Length L Ch R = 1 ,907.4   ,237,241.7,245
XS GIS Cut Line= 4
     2371794.891      386220.095     2371966.332      386196.224
     2372041.201      385860.576     2372035.776      385807.407
#Sta/Elev= 30
       0  507.39    15.7  502.83    39.3   497.4    62.9  495.32    78.7  494.47
    90.5  494.11  115.37494.4112     118   494.6   133.8  493.31   173.1  492.63
   213.1  493.34   225.1  492.78   293.1   493.2     317  492.37     361  492.13
     369   491.4     393  491.73     413  490.52     433  490.67     441  489.91
     457  489.52     473  489.81   477.4  490.43     481  491.52     489  494.97
  505.45499.4683     517  503.14   532.3  509.89   543.7  514.24   570.4   523.5
#Mann= 5 ,-1 , 0
       0     .12       0  115.37     .08       0     441    .045       0
   477.4     .08       0  505.45     .12       0
Bank Sta=441,477.4
XS Rating Curve= 0 ,0
Exp/Cntr=0.3,0.1

Type RM Length L Ch R = 1 ,665.7   ,252.9,260.7,268.3
XS GIS Cut Line= 4
     2372058.693      386243.598     2372142.606      386206.983
     2372265.435      385868.381     2372278.455      385800.022
#Sta/Elev= 30
       0  492.44    11.9  492.46    35.8  491.71    51.8  492.07    67.7  491.52
    79.6  492.04   96.35491.6136   174.7  490.61   186.6  490.07  201.81490.3805
   226.1   489.6     238  488.64   249.9  489.47   257.8  488.66   266.1  487.02
   269.7  486.69   277.6   486.8   281.1  487.32   285.5  488.54   289.5  489.06
   301.3  488.39     333  490.34  351.41 490.877   384.5  491.82   400.3  492.75
   435.9  493.29   451.8  494.79   463.3   497.1   471.1   499.5   521.3  520.61
#Mann= 6 ,-1 , 0
       0     .08       0   96.35     .12       0  201.81     .08       0
   266.1    .045       0   281.1     .08       0  351.41     .12       0
Bank Sta=266.1,281.1
XS Rating Curve= 0 ,0
Exp/Cntr=0.3,0.1

Type RM Length L Ch R = 1 ,404.9   ,338.9,350,361.1
XS GIS Cut Line= 3
     2372135.733      386245.768     2372330.915      386092.328
     2372493.806      385900.716
#Sta/Elev= 30
       0  492.05    11.8   491.2    19.7  491.96    27.6  492.22    78.8  491.59
    94.6  491.94   106.4  491.57   118.2  490.38   137.9  489.52   149.8  489.98
   161.6  490.96  196.76491.1725   244.3   490.8   268.2  489.58   303.2489.7075
   340.1  490.18   348.1   489.1   356.1  487.05     360  486.55   368.6   486.4
     380  485.43     384  485.51     388  486.35     392  487.22     396  487.55
   419.9  487.42   431.9  489.76   451.9  496.01   463.8  500.69   499.8  516.18
#Mann= 5 ,-1 , 0
       0     .12       0  196.76     .08       0   303.2     .12       0
   368.6    .045       0     388     .12       0
Bank Sta=368.6,388
XS Rating Curve= 0 ,0
Exp/Cntr=0.3,0.1

Type RM Length L Ch R = 1 ,55      ,37.2,55,72.3
XS GIS Cut Line= 2
     2372483.606       386308.63     2372762.252      386204.463
#Sta/Elev= 30
       0  487.72    19.8  487.94    43.6  488.89    47.6  488.75    51.6  488.17
    55.5  487.16    59.5  486.57    67.4  486.65    95.2  485.84    99.2  485.42
   107.1  483.84     115  483.85     123  485.76   126.9   486.4   130.9  486.44
   134.9  486.24   156.4  484.07   162.6  483.41   166.6   483.6   171.4  484.26
   174.5  485.15   178.5  488.59   182.4  492.92   186.4  495.72   206.2  504.03
   222.1  508.99   245.9   514.4   261.8  518.92   281.6  523.82   297.5  528.79
#Mann= 3 ,-1 , 0
       0     .12       0   156.4    .045       0   171.4     .12       0
Bank Sta=156.4,171.4
XS Rating Curve= 0 ,0
Exp/Cntr=0.3,0.1

Chan Stop Cuts=-1
Use User Specified Reach Order=0
Composite Channel Slope=5